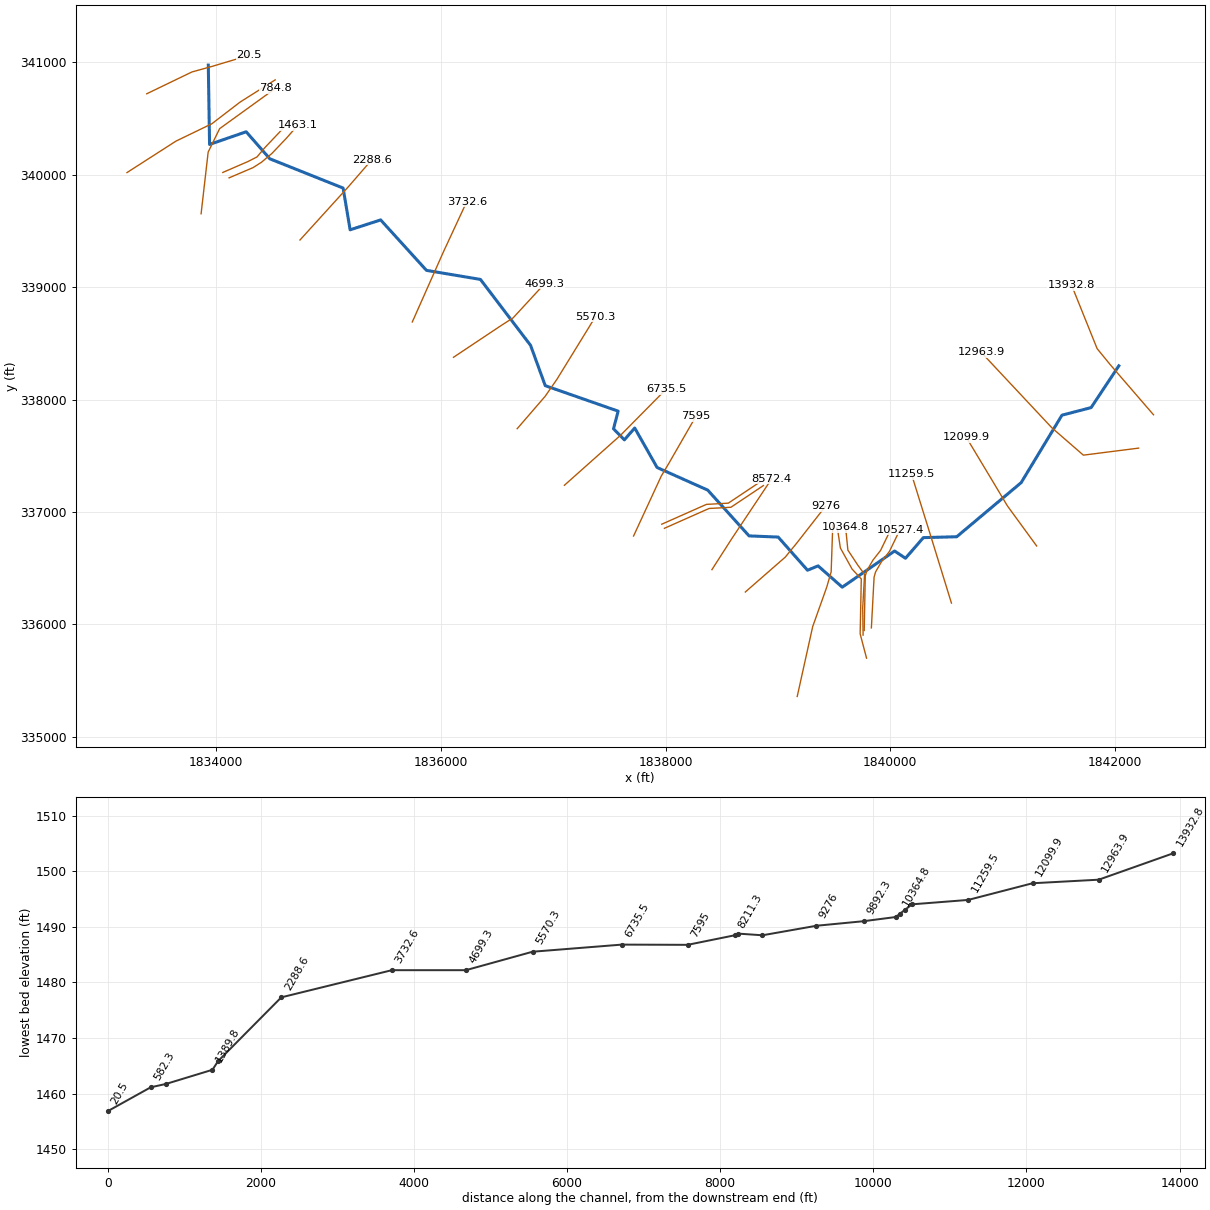
--- WhtDayCrk.prj (project) ---

Proj Title=WhtDayCrk
Current Plan=p01
Default Exp/Contr=0,0
English Units
Geom File=g01
Flow File=f01
Plan File=p01
BEGIN DESCRIPTION:
END DESCRIPTION:
DSS Export Rating Curves= 0
DSS Export Rating Curve Sorted= 0
DSS Export Volume Flow Curves= 0
DXF OffsetX= 0
DXF OffsetY= 0
DXF ScaleX= 0
DXF ScaleY= 0

--- WhtDayCrk.p01 (plan) ---

Plan Title=Floodplain
Program Version=4.00
Geom File=g01
Flow File=f01
K Sum by GR=0
Std Step Tol=0.01
Critical Tol=0.01
Num of Std Step Trials=20
Max Error Tol=0.3
Flow Tol Ratio=0.001
Split Flow NTrial=30
Split Flow Tol=0.02
Split Flow Ratio=0.02
Log Output Level=0
Friction Slope Method=1
Unsteady Friction Slope Method=2
Unsteady Bridges Friction Slope Method=1
Global Log Level=0
CheckData=False
Run HTab=0
Run UNet=0
Run PostProcess=0
UNET Theta=0
UNET Theta Warmup=0
UNET ZTol=0
UNET ZSATol=0
UNET MxIter=0
UNET MaxInSteps=0
UNET DtIC=0
UNET DtMin=0
UNET MaxCRTS=0
UNET WFStab=0
UNET SFStab=0
UNET WFX=0
UNET SFX=0
UNET DSS MLevel=0
UNET DZMax Abort=0
UNET Convert EG Bridges=0
UNET Use Existing IB Tables=0
UNET Froude Limit=0
UNET Froude Power=0
Write IC File=0
Echo Input=False
Echo Output=False
Write Detailed=0

--- WhtDayCrk.f01 (steady flow) ---

Flow Title=NFF Regression Equation
Program Version=4.10
Number of Profiles= 1
Profile Names=P100yr
River Rch & RM=WhtDayCrk,Main            ,13932.8
     876
River Rch & RM=WhtDayCrk,Main            ,10364.8
     945
River Rch & RM=WhtDayCrk,Main            ,9892.3
    1094
River Rch & RM=WhtDayCrk,Main            ,8254.8
    1116
River Rch & RM=WhtDayCrk,Main            ,6735.5
    1235
River Rch & RM=WhtDayCrk,Main            ,784.8
    1369
River Rch & RM=WhtDayCrk,Main            ,582.3
    2008
River Rch & RM=WhtDayCrk,Main            ,20.5
    2043
Boundary for River Rch & Prof#=WhtDayCrk,Main            , 1
Up Type= 0
Dn Type= 3
Dn Slope=0.00316
DSS Import GetInterval= 0
DSS Import GetPeak= 0
DSS Import FillOption= 0

--- WhtDayCrk.g01 (geometry) ---

Geom Title=USGS 10m DEM
Program Version=4.10

River Reach=WhtDayCrk       ,Main
Reach XY= 30
     1842034.588      338299.484     1841787.884      337928.027
     1841528.283      337860.508     1841165.136      337260.546
     1840591.271      336779.001     1840294.556      336771.183
     1840135.172      336587.455     1840038.353      336652.034
     1839572.204      336330.299     1839357.089      336519.831
     1839263.148      336481.077     1839001.924      336776.045
     1838742.538      336786.616     1838374.524      337194.027
      1837923.96       337394.92     1837724.611      337746.378
     1837632.545      337641.098     1837535.883      337739.533
     1837577.139       337896.46     1836928.277      338123.129
     1836797.555      338481.679     1836351.159      339068.314
      1835870.66      339148.985     1835462.908      339597.613
      1835190.99      339509.721      1835128.74      339881.151
     1834476.748      340141.202     1834265.402      340381.919
     1833939.788      340269.187     1833928.548      340974.747

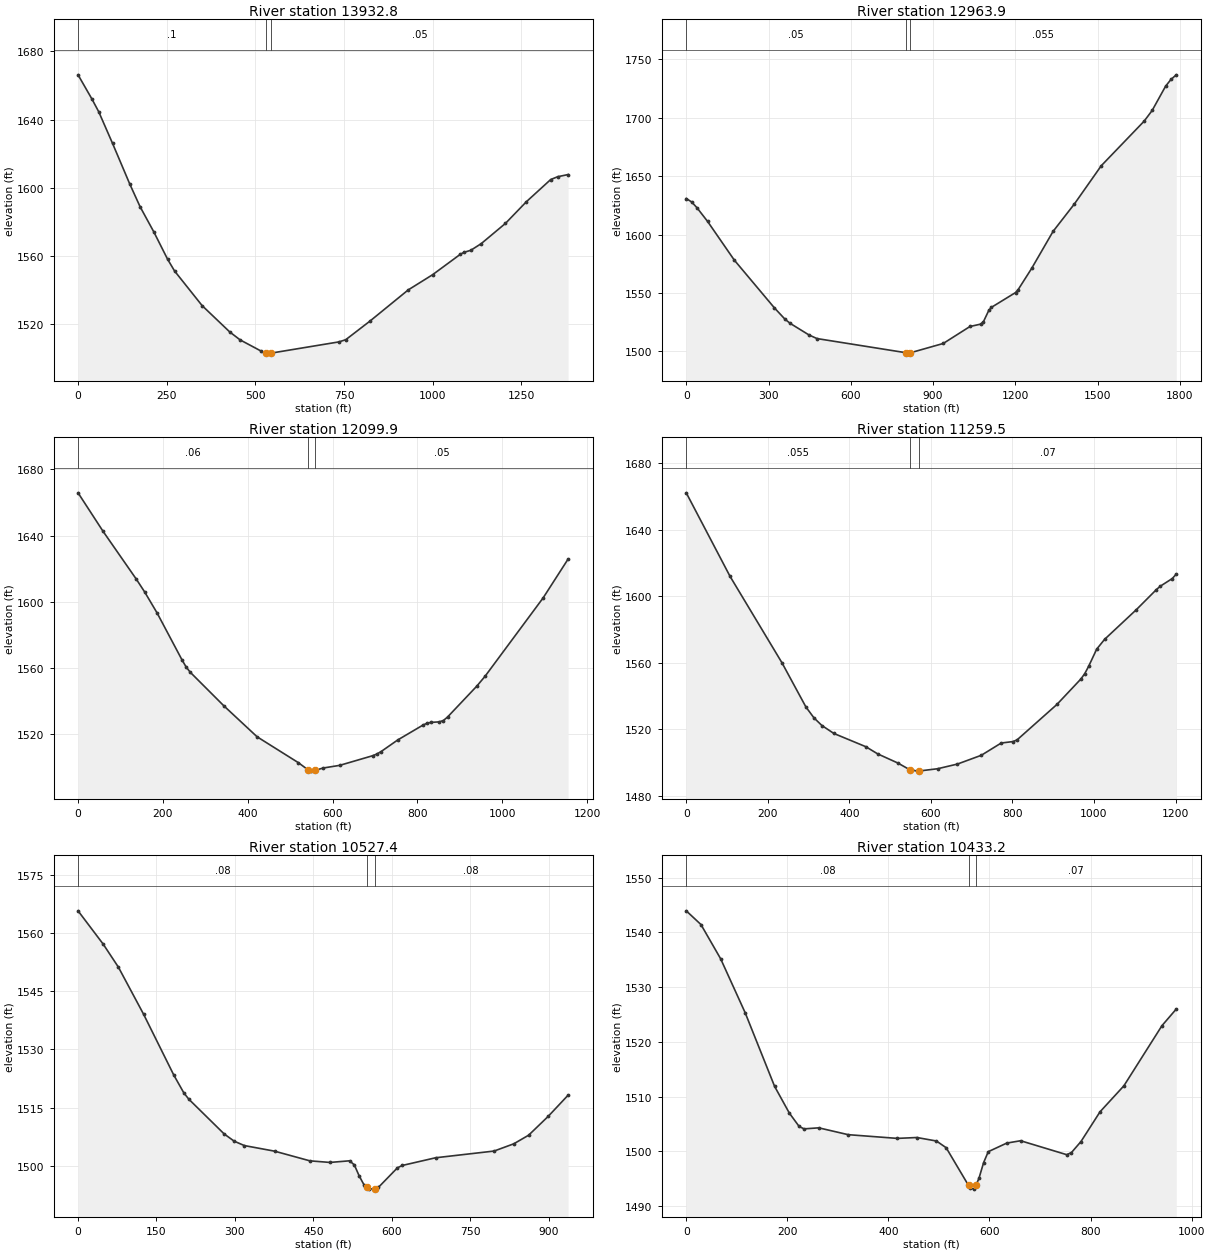
Type RM Length L Ch R = 1 ,13932.8 ,952.9,968.9,973
XS GIS Cut Line= 4
     1842343.372      337863.919     1841955.883      338312.401
     1841841.263      338452.741     1841614.206      339016.262
#Sta/Elev= 30
       0 1666.24    38.9 1652.16    58.3 1644.61    97.2 1626.11   145.7 1602.33
   174.9 1588.98   213.8 1574.15   252.6 1558.16   272.1 1551.33   349.8 1531.04
   427.5 1515.65   456.7 1510.99     515 1504.53   528.9 1503.47   543.9 1503.21
  544.56 1503.23   735.7  1509.8   754.8 1511.09   822.9 1521.97   930.7 1540.23
   999.3 1549.12  1077.7 1561.11  1087.5 1562.23  1107.1 1563.44  1136.5 1567.34
    1205 1579.23  1263.8 1591.89  1332.4  1604.9    1352 1606.54  1381.4 1607.82
#Mann= 3 , 0 , 0
       0      .1       0   528.9    .045       0  544.56     .05       0
Bank Sta=528.9,544.56
XS Rating Curve= 0 ,0
Exp/Cntr=0.3,0.1

Type RM Length L Ch R = 1 ,12963.9 ,864.7,864,850.6
XS GIS Cut Line= 4
     1842210.912       337567.47     1841718.724       337504.97
     1841437.654      337749.033      1840809.87      338419.032
#Sta/Elev= 30
       0 1630.85    19.5 1627.93    38.9 1623.02    77.8 1611.24   175.1 1578.15
     321 1537.33   359.9 1527.54   379.4 1523.88   447.5 1514.03   476.7 1510.94
   799.6 1498.88   809.6 1498.48   814.6 1498.61   936.8 1506.74  1034.4 1521.28
  1073.5 1523.32  1083.3 1525.31  1102.8 1534.98  1112.6 1537.68  1200.5 1550.33
  1210.2 1552.92  1259.1 1570.97  1337.2 1602.66  1415.4  1626.3    1513 1658.92
  1669.3 1697.08  1698.6 1706.25  1747.5    1727    1767 1732.77  1786.5 1736.76
#Mann= 3 , 0 , 0
       0     .05       0   799.6    .045       0   814.6    .055       0
Bank Sta=799.6,814.6
XS Rating Curve= 0 ,0
Exp/Cntr=0.3,0.1

Type RM Length L Ch R = 1 ,12099.9 ,843.6,840.4,825.3
XS GIS Cut Line= 4
     1841302.839      336696.918     1841042.422      337053.689
      1840922.63       337254.21     1840675.235      337665.668
#Sta/Elev= 30
       0  1665.8    58.9  1642.6   137.4 1613.69     157    1606   186.5 1593.25
   245.4 1564.84   255.2 1560.54     265 1557.41   343.6  1537.3   422.1 1518.58
   519.6 1502.92   542.2 1498.65   548.8 1497.84   558.5 1498.29     578 1499.72
   616.9 1501.32   694.9 1507.16   704.7 1508.17   714.5 1509.64   753.7 1516.64
   812.5 1525.51   822.2 1526.69     832 1527.26   851.6 1527.57   861.4 1528.38
   871.2 1530.48   939.8 1549.03   959.4 1554.99  1096.6 1602.39  1155.4  1625.8
#Mann= 3 , 0 , 0
       0     .06       0   542.2    .045       0   558.5     .05       0
Bank Sta=542.2,558.5
XS Rating Curve= 0 ,0
Exp/Cntr=0.3,0.1

Type RM Length L Ch R = 1 ,11259.5 ,746.4,732.1,679.3
XS GIS Cut Line= 3
     1840544.327      336188.571     1840379.895      336721.606
     1840188.425      337336.575
#Sta/Elev= 30
       0 1662.19   107.6 1611.88   234.9 1559.94   293.6 1533.38   313.2 1526.89
   332.7 1522.27   362.1 1517.49   440.4 1509.53   469.7 1505.19   518.7 1499.75
     548 1495.71   567.6 1494.84  569.84 1494.88   616.4 1496.27   665.2 1499.09
   723.7 1504.37   772.5 1511.74   801.8 1512.63   811.6 1513.67   909.1 1534.92
   967.7 1550.18   977.4 1553.45   987.2 1557.99  1006.7  1568.2  1026.2 1574.11
  1104.3 1592.01  1153.1    1604  1162.9 1606.08  1192.2 1610.66  1201.9 1613.34
#Mann= 3 , 0 , 0
       0    .055       0     548    .045       0  569.84     .07       0
Bank Sta=548,569.84
XS Rating Curve= 0 ,0
Exp/Cntr=0.3,0.1

Type RM Length L Ch R = 1 ,10527.4 ,90.9,94.2,119.8
XS GIS Cut Line= 6
     1839831.547      335968.209     1839855.771      336420.487
     1839869.226      336466.494     1839924.348      336561.546
      1839991.94      336647.599     1840086.385      336842.738
#Sta/Elev= 30
       0 1565.67    48.2 1557.08    77.1 1551.19   125.3 1539.07   183.1  1523.4
   202.4 1518.79     212 1517.17   279.5 1508.24   298.7 1506.38     318 1505.26
   375.8 1503.82   443.3 1501.33   481.7 1500.92   519.2 1501.34   528.3 1500.29
   537.5 1497.47   546.6  1495.2   551.9 1494.62   555.8  1494.2     565 1494.05
   566.9 1494.14   574.1 1494.47   610.7 1499.53   619.9 1500.14   683.7 1502.12
   795.6 1503.85   833.3 1505.72   861.6 1507.93   899.2  1512.8     937 1518.22
#Mann= 3 , 0 , 0
       0     .08       0   551.9    .045       0   566.9     .08       0
Bank Sta=551.9,566.9
XS Rating Curve= 0 ,0
Exp/Cntr=0.3,0.1

Type RM Length L Ch R = 1 ,10433.2 ,36.9,68.4,95.8
XS GIS Cut Line= 6
     1839767.745      335944.771     1839777.299      336430.209
     1839790.754      336476.216     1839845.875      336571.268
     1839913.468      336657.321     1840007.912       336852.46
#Sta/Elev= 30
       0 1543.96    29.1 1541.45      68  1535.2   116.5 1525.34   174.8 1511.86
   203.9 1506.98   223.3 1504.53   233.1 1504.08   262.2 1504.27   320.4 1503.02
   417.6 1502.34   456.4  1502.5   495.1 1501.86   514.3 1500.63   558.5 1493.74
   560.9 1493.27   570.1 1493.06   573.5  1493.8   579.2 1495.05   588.4 1497.91
   597.6 1499.91   634.2 1501.48   661.6 1501.91   752.8 1499.36   762.2 1499.75
     781 1501.76   818.8 1507.21   865.9 1511.95   941.3 1522.96   969.6    1526
#Mann= 3 , 0 , 0
       0     .08       0   558.5    .045       0   573.5     .07       0
Bank Sta=558.5,573.5
XS Rating Curve= 0 ,0
Exp/Cntr=0.3,0.1

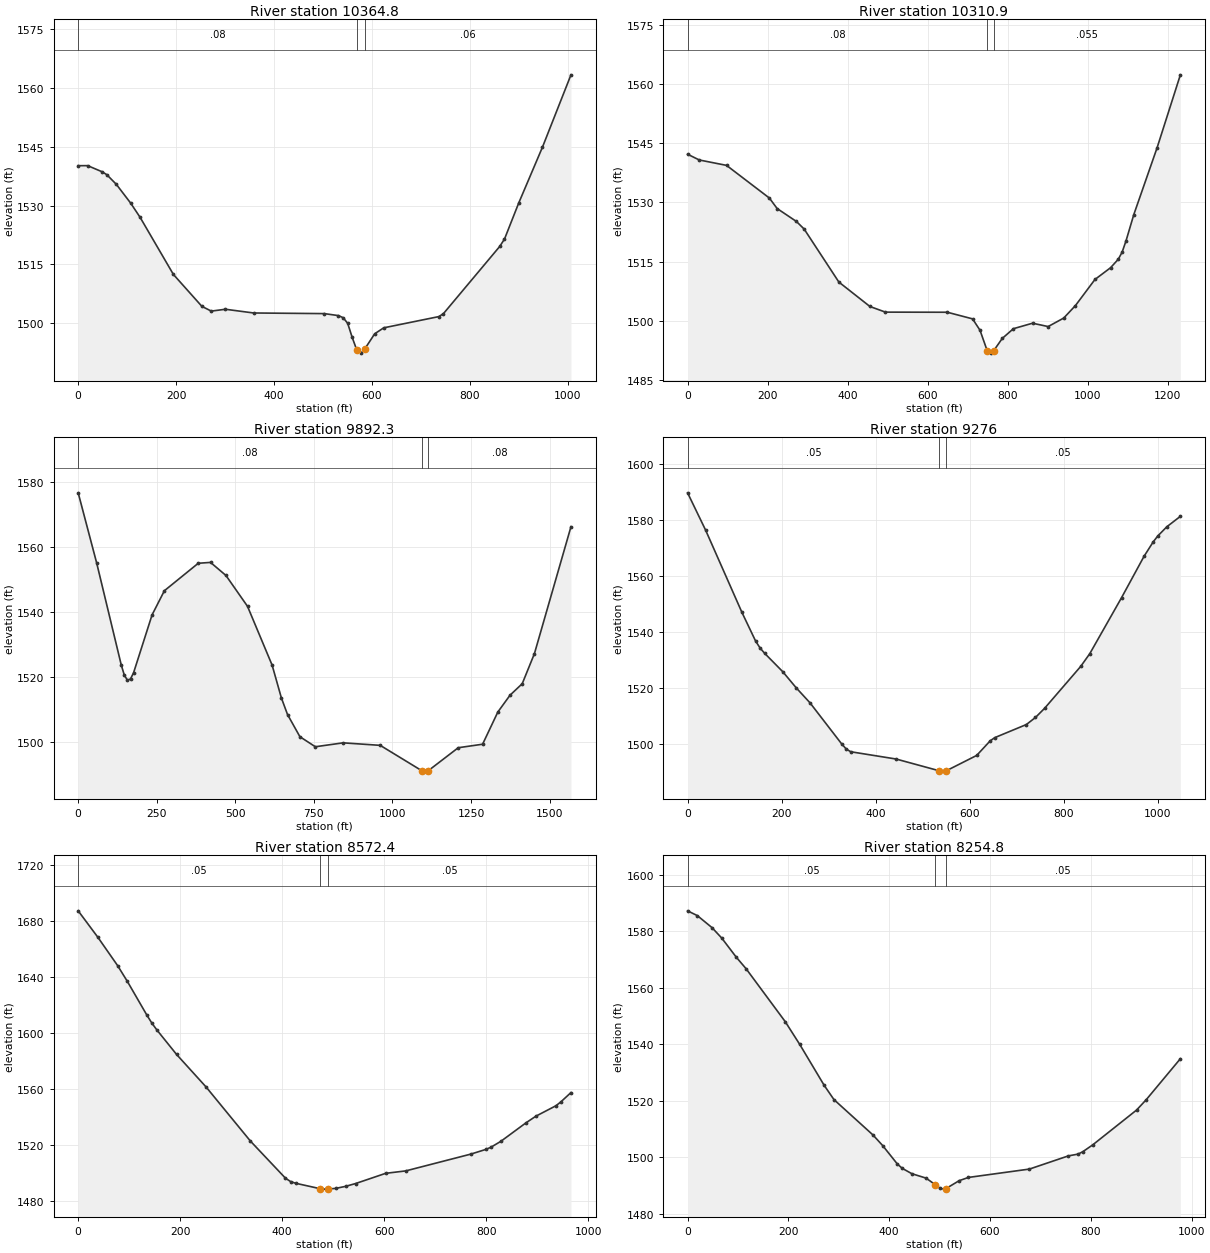
Type RM Length L Ch R = 1 ,10364.8 ,51,53.9,56.2
XS GIS Cut Line= 6
     1839757.898      335903.738     1839754.426      336146.793
     1839770.919      336444.536     1839711.023      336526.134
     1839622.481      336659.814     1839602.082      336862.505
#Sta/Elev= 30
       0 1540.18    19.4 1540.19    48.6 1538.64    58.3  1537.9    77.8 1535.44
     107 1530.66   126.4 1527.01   194.5 1512.41   252.7 1504.26   271.9 1503.05
   300.8 1503.52   358.5 1502.57   502.8 1502.41   531.7  1501.9   541.3 1501.36
   550.5 1499.93   559.7 1496.34   568.9 1493.18   570.2 1493.06   578.1 1492.32
   585.2 1493.35   605.7 1497.26   624.1 1498.78   736.8 1501.65   746.2 1502.42
     861 1519.55   870.8 1521.44   899.8 1530.63   948.4 1544.92  1006.6 1563.38
#Mann= 3 , 0 , 0
       0     .08       0   570.2    .045       0   585.2     .06       0
Bank Sta=570.2,585.2
XS Rating Curve= 0 ,0
Exp/Cntr=0.3,0.1

Type RM Length L Ch R = 1 ,10310.9 ,386.2,418.5,389.2
XS GIS Cut Line= 6
     1839788.578      335698.678     1839731.593      335915.241
     1839741.736      336403.126     1839659.705      336491.667
     1839555.538      336679.167     1839528.195      336861.459
#Sta/Elev= 30
       0 1542.22    29.2 1540.76    97.4 1539.39   204.5  1531.1   223.9 1528.44
   272.1 1525.16   291.4 1523.24   378.2 1509.79   455.9 1503.59   494.7 1502.16
   649.4 1502.13   712.5 1500.45   731.1 1497.56   749.6 1492.21   758.9 1491.76
   765.4 1492.39   786.8  1495.5   814.6 1497.96   862.4 1499.35   901.4  1498.5
   940.4 1500.66   969.7 1503.83  1018.4 1510.44  1057.4 1513.42  1076.8 1515.58
  1086.5 1517.41  1096.2 1520.27  1115.6 1526.91  1173.8 1543.86    1232 1562.36
#Mann= 3 , 0 , 0
       0     .08       0   749.6    .045       0   765.4    .055       0
Bank Sta=749.6,765.4
XS Rating Curve= 0 ,0
Exp/Cntr=0.3,0.1

Type RM Length L Ch R = 1 ,9892.3  ,569.7,616.3,585.3
XS GIS Cut Line= 5
     1839171.304      335358.009      1839309.11      335979.679
     1839434.445      336331.511     1839473.507      336466.928
      1839487.83      336883.594
#Sta/Elev= 30
       0 1576.52    58.8 1554.98   137.2 1523.58   146.9 1520.48   156.7 1518.95
   166.5 1519.34   176.3 1521.24   235.1 1539.01   274.3 1546.44   382.1 1554.88
   421.2 1555.14   470.2 1551.13   538.8 1541.65   617.2 1523.56   646.6  1513.5
   666.2 1508.39   705.6 1501.58   754.7  1498.5   843.2  1499.7   961.1 1498.93
  1094.8 1491.06  1104.2 1491.01  1113.6 1491.11  1209.4  1498.2  1286.9 1499.28
  1335.4 1509.17  1374.2 1514.34    1413 1517.87  1451.8 1527.11  1568.1 1566.11
#Mann= 3 , 0 , 0
       0     .08       0  1094.8    .045       0  1113.6     .08       0
Bank Sta=1094.8,1113.6
XS Rating Curve= 0 ,0
Exp/Cntr=0.3,0.1

Type RM Length L Ch R = 1 ,9276    ,663.4,703.6,707.9
XS GIS Cut Line= 4
     1838709.184       336287.24     1839065.087      336598.004
     1839167.518      336723.004     1839422.726      337049.393
#Sta/Elev= 30
       0 1589.73    38.6  1576.3   115.7 1546.94   144.6 1536.75   154.3 1534.21
   163.9 1532.34   202.5 1525.75   231.4 1519.93   260.4 1514.63   327.8 1499.93
   337.5 1498.11   347.1 1497.12   443.6 1494.52     535 1490.33     539 1490.19
     550 1490.28   615.1 1495.81   643.7 1501.01   653.4 1502.16   720.8 1506.86
   740.1 1509.38   759.4 1512.63   836.4 1527.65   855.7 1532.21   923.2 1552.21
   971.3 1567.08   990.6 1572.18  1000.2 1574.27  1019.5 1577.58  1048.4 1581.32
#Mann= 3 , 0 , 0
       0     .05       0     535    .045       0     550     .05       0
Bank Sta=535,550
XS Rating Curve= 0 ,0
Exp/Cntr=0.3,0.1

Type RM Length L Ch R = 1 ,8572.4  ,327,317.7,280.3
XS GIS Cut Line= 3
     1838412.205      336486.518     1838589.288       336762.56
     1838943.455       337293.81
#Sta/Elev= 30
       0 1687.37    38.6 1668.47    77.2 1648.29    96.5  1636.9     135 1612.65
   144.7 1607.01   154.3 1602.25   192.9 1584.76   250.8 1561.49   337.8 1522.81
   406.5  1496.3   416.4 1493.92   426.2  1492.7   474.8 1488.76   485.1 1488.48
   489.8 1488.56   504.8 1488.99   524.4 1490.46   544.1 1492.48     603 1499.77
   642.3  1501.5     770 1513.51   799.4 1516.86   809.3  1518.4   828.9 1522.64
     878 1535.82   897.7 1540.63     937 1548.08   946.8 1550.91   966.4 1557.49
#Mann= 3 , 0 , 0
       0     .05       0   474.8    .045       0   489.8     .05       0
Bank Sta=474.8,489.8
XS Rating Curve= 0 ,0
Exp/Cntr=0.3,0.1

Type RM Length L Ch R = 1 ,8254.8  ,42.5,43.5,49.6
XS GIS Cut Line= 6
     1837989.012      336854.103      1838360.54      337019.034
     1838387.247      337030.527      1838499.66      337036.603
     1838581.257      337041.377     1838870.537      337234.444
#Sta/Elev= 30
       0 1587.31    19.4 1585.61    48.4 1581.37    67.8 1577.66    96.8 1570.85
   116.1 1566.81   193.6 1548.11   222.6 1539.99     271 1525.53   290.4 1520.48
   367.8 1507.96   387.1 1504.19   416.2 1497.67   425.9 1496.14     445 1494.24
   473.1 1492.68   491.8  1490.3   501.2 1489.02   510.6 1488.78   511.9 1488.89
   538.8 1491.77   557.2 1492.92   678.2 1495.88   755.5 1500.55   774.8 1501.18
   784.4 1502.06   803.8 1504.45   890.7 1516.76     910 1520.45   977.7 1534.95
#Mann= 3 , 0 , 0
       0     .05       0   491.8    .045       0   511.9     .05       0
Bank Sta=491.8,511.9
XS Rating Curve= 0 ,0
Exp/Cntr=0.3,0.1

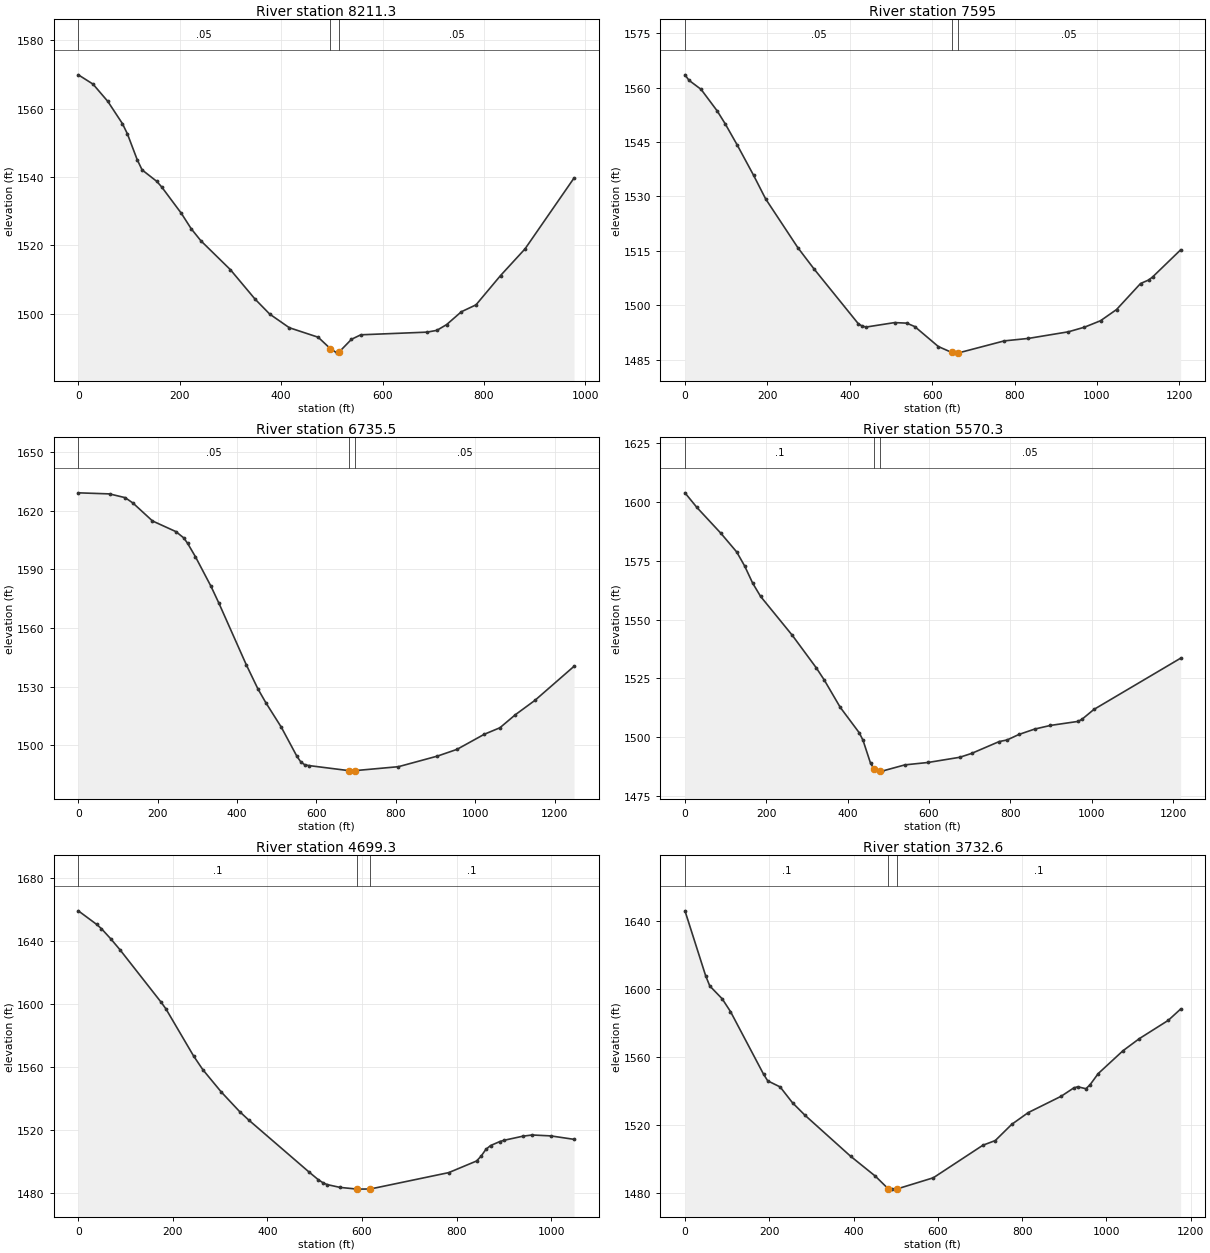
Type RM Length L Ch R = 1 ,8211.3  ,583.4,616.3,637.3
XS GIS Cut Line= 6
     1837965.575      336890.561     1838337.102      337055.492
      1838363.81      337066.985     1838476.223      337073.061
      1838557.82      337077.836     1838847.099      337270.902
#Sta/Elev= 30
       0 1569.88      29 1567.16    58.1 1562.12    87.1 1555.58    96.8 1552.61
   116.1 1545.07   125.8 1542.07   154.8 1538.71   164.5 1537.07   203.2 1529.37
   222.6 1524.87     242  1521.3     300 1512.88   348.4 1504.31   377.5  1499.9
   416.2 1495.91   473.1 1493.13     497 1489.81   510.6 1488.48  514.69 1488.85
   538.8 1492.53   557.2 1493.84   687.8 1494.62   707.2 1495.14   726.5 1496.83
   755.5 1500.58   784.4  1502.6   832.8 1511.17   881.1 1518.97   977.7 1539.68
#Mann= 3 , 0 , 0
       0     .05       0     497    .045       0  514.69     .05       0
Bank Sta=497,514.69
XS Rating Curve= 0 ,0
Exp/Cntr=0.3,0.1

Type RM Length L Ch R = 1 ,7595    ,754.5,859.5,770.4
XS GIS Cut Line= 4
     1837714.393      336785.504      1837960.92       337318.49
     1838032.101      337438.282     1838269.948      337851.476
#Sta/Elev= 30
       0 1563.59     9.8 1562.08    39.2 1559.57    78.3 1553.62    97.9 1550.03
   127.2 1544.15   166.4  1535.9   195.8 1529.35     274 1515.88   313.2 1510.02
   420.8 1494.88   430.6  1494.2   440.4 1493.97   508.9 1495.19   538.3 1495.04
   557.9 1494.09   615.1 1488.58   647.6 1486.95   661.6 1486.76   662.6 1486.78
   775.2 1490.14   833.6 1490.82   930.9 1492.65   969.8 1493.92  1008.8  1495.7
  1047.7 1498.79    1106 1505.98  1125.5 1506.94  1135.2 1507.78  1203.3 1515.27
#Mann= 3 , 0 , 0
       0     .05       0   647.6    .045       0   662.6     .05       0
Bank Sta=647.6,662.6
XS Rating Curve= 0 ,0
Exp/Cntr=0.3,0.1

Type RM Length L Ch R = 1 ,6735.5  ,1046.5,1165.2,1094.6
XS GIS Cut Line= 3
     1837098.801       337237.05     1837598.507      337681.772
     1838006.493      338094.098
#Sta/Elev= 30
       0 1629.15    78.7  1628.6     118 1626.68   137.7 1623.92   186.9 1614.76
   245.9 1609.31   265.6  1606.1   275.4 1603.31   295.1 1596.46   334.5 1581.25
   354.2 1572.72     423 1541.31   452.5 1528.88   472.2  1521.9   511.5 1509.26
   550.9 1494.34   560.7 1491.48   570.6 1490.05   580.4 1489.66   682.3 1487.04
   688.6  1486.8   698.4 1487.08   806.6 1489.07   904.9 1494.49     954 1497.92
  1022.9 1505.65  1062.2 1508.97  1101.5 1515.69  1150.7 1523.02    1249  1540.4
#Mann= 3 , 0 , 0
       0     .05       0   682.3    .045       0   698.4     .05       0
Bank Sta=682.3,698.4
XS Rating Curve= 0 ,0
Exp/Cntr=0.3,0.1

Type RM Length L Ch R = 1 ,5570.3  ,864.8,871,852.6
XS GIS Cut Line= 4
     1836678.368      337740.365     1836927.934      338028.994
     1837034.271      338183.074     1837374.983      338736.459
#Sta/Elev= 30
       0 1603.95    29.4 1597.72      88  1586.8   127.2 1578.79   146.8 1572.81
   166.3 1565.57   185.9 1559.88   264.2 1543.25   322.9 1529.46   342.4 1524.32
   381.6 1512.71   428.4 1501.86   437.7 1498.67   456.4  1488.8   465.8  1486.3
   478.5 1485.55   484.5 1485.52   540.7 1488.18   597.9 1489.21   675.5 1491.41
   704.6 1493.05   772.5  1498.1   791.9 1498.78     821 1501.12   859.8 1503.42
   898.6 1504.97   966.4 1506.68   976.2  1507.6  1005.2 1511.75  1218.6 1533.58
#Mann= 3 , 0 , 0
       0      .1       0   465.8    .045       0   478.5     .05       0
Bank Sta=465.8,478.5
XS Rating Curve= 0 ,0
Exp/Cntr=0.3,0.1

Type RM Length L Ch R = 1 ,4699.3  ,953.2,966.7,978.8
XS GIS Cut Line= 4
     1836111.283      338375.613     1836541.505      338662.096
     1836642.199      338726.332     1836921.713      339029.283
#Sta/Elev= 30
       0 1659.38      39 1650.69    48.8 1648.05    68.3 1641.66    87.8 1634.72
   175.5 1601.05   185.3 1596.96   243.8 1566.99   263.3 1558.28   302.3 1544.07
   341.3 1531.54   360.8 1526.11   487.6  1493.2   507.1 1488.32   516.9 1486.37
   526.1 1485.11   553.6  1483.3   590.4  1482.2   617.9  1482.3   783.5 1492.71
   842.4 1500.11   852.2 1503.27     862 1507.48   871.9 1509.93   891.5 1512.48
   901.3 1513.35   940.6 1515.92   960.2 1516.67   999.4 1516.09  1048.5  1513.9
#Mann= 3 , 0 , 0
       0      .1       0   590.4    .045       0   617.9      .1       0
Bank Sta=590.4,617.9
XS Rating Curve= 0 ,0
Exp/Cntr=0.3,0.1

Type RM Length L Ch R = 1 ,3732.6  ,1448.5,1444,1430.3
XS GIS Cut Line= 3
      1835744.61      338689.861     1836023.877      339318.176
     1836229.938      339761.283
#Sta/Elev= 30
       0 1646.21    49.1 1607.96    58.9 1601.93    88.4 1594.35     108 1586.88
   186.6  1549.9   196.4 1546.02   225.9 1542.42   255.4 1533.04   284.9 1525.73
   392.9 1501.62   451.8 1489.85   482.3 1482.43   491.1  1482.2  502.04 1482.21
   589.4 1488.89   707.1 1508.08   736.4 1510.82   775.5 1520.38   814.6  1527.3
   892.8 1536.93   922.2 1541.76   931.9 1542.53   951.5 1541.37   961.2 1543.66
   980.8 1550.32  1039.4 1563.74  1078.5 1570.93  1146.9 1581.66  1176.3 1588.33
#Mann= 3 , 0 , 0
       0      .1       0   482.3    .045       0  502.04      .1       0
Bank Sta=482.3,502.04
XS Rating Curve= 0 ,0
Exp/Cntr=0.3,0.1

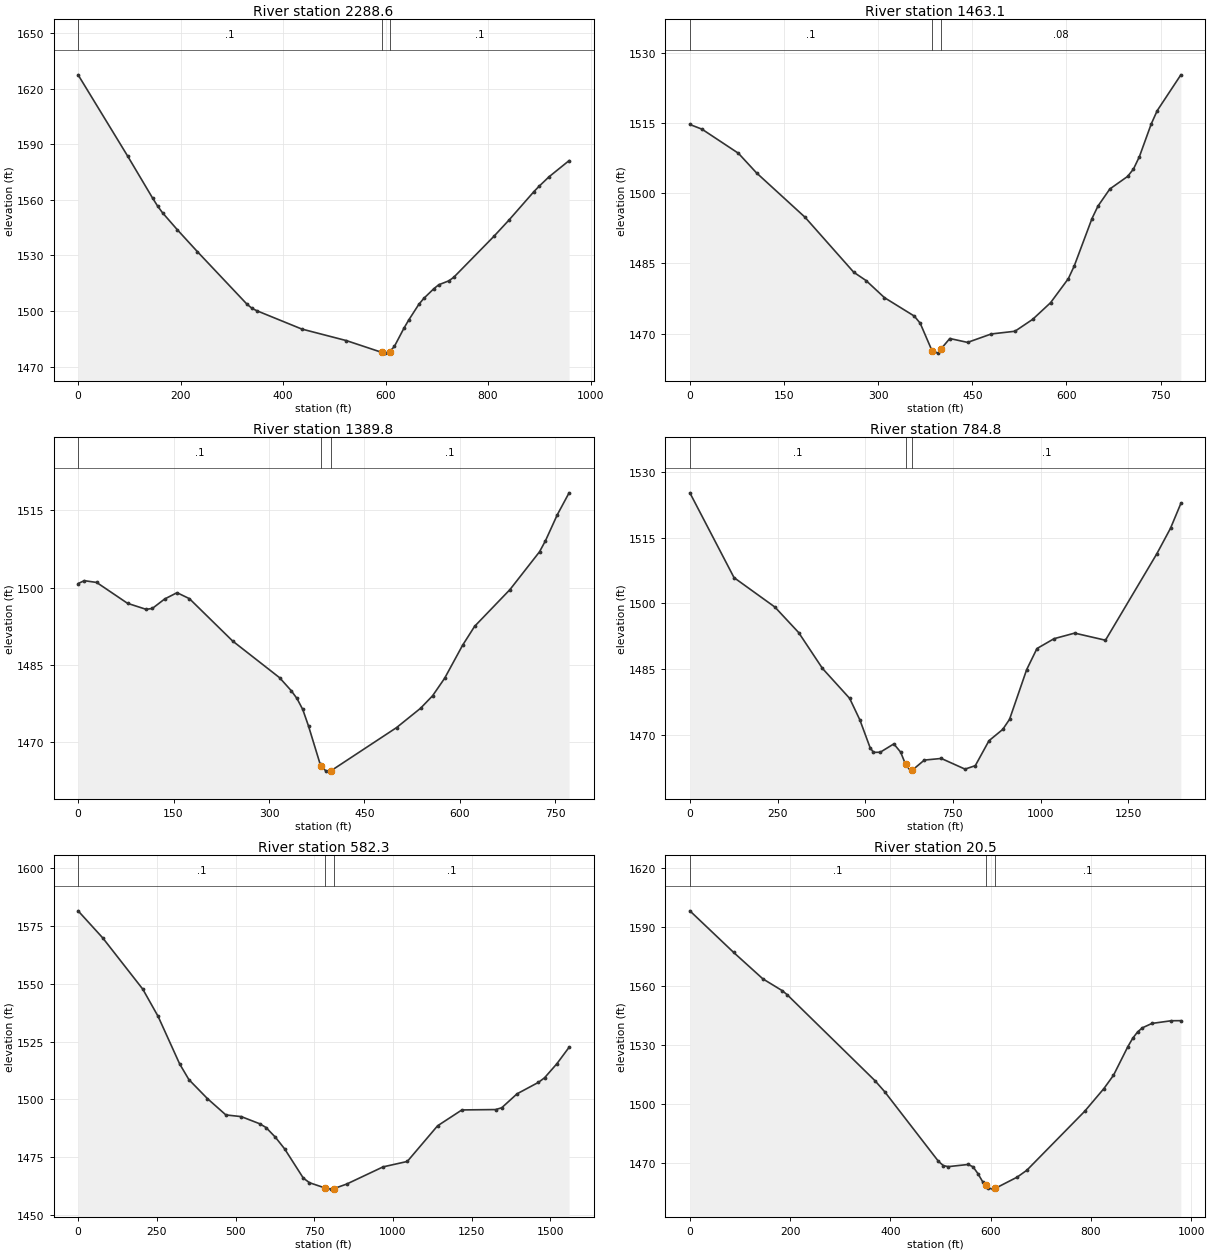
Type RM Length L Ch R = 1 ,2288.6  ,828.6,825.6,821.3
XS GIS Cut Line= 4
     1834744.586      339418.892     1835096.931      339806.471
     1835178.614      339896.322     1835383.692      340132.703
#Sta/Elev= 30
       0 1627.47      97  1583.5   145.5 1560.92   155.2 1556.67   164.9    1553
     194 1543.78   232.8 1532.07   329.8 1503.65   339.5 1501.47   349.2 1500.14
   436.5 1490.31   523.8 1484.05   592.4 1477.74   598.5 1477.31   607.9 1478.09
   617.2  1480.9   635.9 1490.76   645.2 1495.15   664.8 1503.56   674.6 1506.83
   694.1 1512.03   703.9  1514.2   723.5 1516.31   733.2 1518.25   811.5 1540.34
   840.8 1549.08   889.7  1564.5   899.5  1567.3     919 1572.44   958.2 1581.18
#Mann= 3 , 0 , 0
       0      .1       0   592.4    .045       0   607.9      .1       0
Bank Sta=592.4,607.9
XS Rating Curve= 0 ,0
Exp/Cntr=0.3,0.1

Type RM Length L Ch R = 1 ,1463.1  ,69,73.2,76.9
XS GIS Cut Line= 6
     1834113.814      339972.111     1834327.008      340063.083
     1834401.266      340110.232      1834495.02      340189.291
     1834625.229       340326.01     1834724.925      340439.472
#Sta/Elev= 30
       0 1514.64    19.3 1513.64    77.3  1508.5   106.2 1504.31   183.5 1494.84
   261.1  1483.1   280.7 1481.33     310 1477.68   357.5 1473.75   366.9 1472.23
   385.8 1466.34   395.2 1465.84   400.4 1466.79   414.1 1468.96   442.4 1468.13
   480.2 1469.93   517.9 1470.51   546.2 1473.06   574.6  1476.6   602.9 1481.73
   612.3 1484.43   640.6 1494.56   650.1 1497.22     669 1500.87   697.3 1503.55
   706.7 1505.13   716.2  1507.8     735 1514.76   744.5 1517.59   782.2 1525.24
#Mann= 3 , 0 , 0
       0      .1       0   385.8    .045       0   400.4     .08       0
Bank Sta=385.8,400.4
XS Rating Curve= 0 ,0
Exp/Cntr=0.3,0.1

Type RM Length L Ch R = 1 ,1389.8  ,597,605.1,609.8
XS GIS Cut Line= 6
     1834057.564      340020.027     1834280.481      340116.555
     1834362.425      340158.222     1834432.564      340241.555
     1834556.175      340371.416     1834656.175      340481.139
#Sta/Elev= 30
       0 1500.77     9.7 1501.34    29.2 1500.99    77.7 1496.93   106.9 1495.76
   116.6 1495.93     136 1497.77   155.5    1499   174.9 1497.84   242.9 1489.59
   316.5 1482.47   334.8 1479.95   343.9 1478.42     353 1476.28   362.1 1473.04
   380.2  1465.7   382.4 1465.36   389.3 1464.28   397.4 1464.35   500.4 1472.75
   538.1 1476.51     557 1478.94   575.9 1482.34   604.2 1488.78   623.1 1492.46
   678.7 1499.62   725.1 1506.97   734.4 1509.11     753 1514.17   771.5 1518.43
#Mann= 3 , 0 , 0
       0      .1       0   382.4    .045       0   397.4      .1       0
Bank Sta=382.4,397.4
XS Rating Curve= 0 ,0
Exp/Cntr=0.3,0.1

Type RM Length L Ch R = 1 ,784.8   ,217.3,202.5,184
XS GIS Cut Line= 4
     1833864.378      339652.182     1833927.312      340201.227
     1834029.309       340409.56     1834528.441      340769.803
#Sta/Elev= 30
       0 1525.22     126 1505.87   242.4 1499.17   310.2 1493.35   378.1 1485.17
   455.7 1478.33   484.8 1473.42   513.9 1467.11   523.6 1466.02   542.9 1466.05
   581.6 1467.95     601 1466.08   615.2 1463.27     630 1461.74  634.73 1461.99
   668.6 1464.26     717 1464.63   784.6  1462.2   813.9 1462.98     853 1468.68
   892.1 1471.25   911.6 1473.55   960.5  1484.9   989.8  1489.7  1038.6 1491.95
  1097.3 1493.22  1185.2  1491.6  1331.8 1511.34  1370.8 1517.16  1400.2 1522.81
#Mann= 3 , 0 , 0
       0      .1       0   615.2    .045       0  634.73      .1       0
Bank Sta=615.2,634.73
XS Rating Curve= 0 ,0
Exp/Cntr=0.3,0.1

Type RM Length L Ch R = 1 ,582.3   ,564.4,561.8,556.3
XS GIS Cut Line= 5
     1833204.656      340018.935     1833640.854      340298.883
     1833959.864      340452.963       1834211.6      340646.105
       1834524.1      340843.588
#Sta/Elev= 30
       0 1581.59    78.2 1569.88   205.4  1547.7   254.3 1535.85   322.7 1515.28
   352.1  1508.5   410.7 1500.32   469.4 1493.24   518.3 1492.51   577.4 1489.39
     597 1487.78   626.6  1483.6   656.1 1478.53   715.1 1465.95   734.8  1463.9
     784 1461.64   803.4 1461.12   813.5 1461.39   852.9  1463.3   968.7 1470.75
  1045.6  1473.1  1141.8 1488.53    1219  1495.4  1326.1 1495.56  1345.5 1496.34
  1394.2 1502.37  1462.3 1507.35  1481.7 1509.33  1520.6 1515.38  1559.5 1522.52
#Mann= 3 , 0 , 0
       0      .1       0     784    .045       0   813.5      .1       0
Bank Sta=784,813.5
XS Rating Curve= 0 ,0
Exp/Cntr=0.3,0.1

Type RM Length L Ch R = 1 ,20.5    ,27.1,20.5,13.9
XS GIS Cut Line= 4
     1833380.437       340719.89     1833782.716      340913.916
     1833962.837       340963.83     1834294.066      341062.772
#Sta/Elev= 30
       0 1598.43    87.4 1577.24   145.6 1563.81   184.5 1557.76   194.2 1555.71
     369 1512.05   388.4 1506.43   495.8 1470.95   505.6 1468.77   515.5 1468.27
   554.8 1469.36   564.7 1468.19   574.5  1464.7   584.4 1460.36   590.2 1458.67
   594.2 1457.51     604 1456.82  609.13 1457.22   652.7 1462.92   671.9  1466.4
   787.2 1496.38   825.6 1507.96   844.8 1514.74   873.6 1529.38   883.2 1533.59
   892.8 1536.78   902.4  1538.9   921.6 1541.14     960  1542.5   979.2 1542.54
#Mann= 3 , 0 , 0
       0      .1       0   590.2    .045       0  609.13      .1       0
Bank Sta=590.2,609.13
XS Rating Curve= 0 ,0
Exp/Cntr=0.3,0.1

Chan Stop Cuts=-1
Use User Specified Reach Order=0
Composite Channel Slope=5